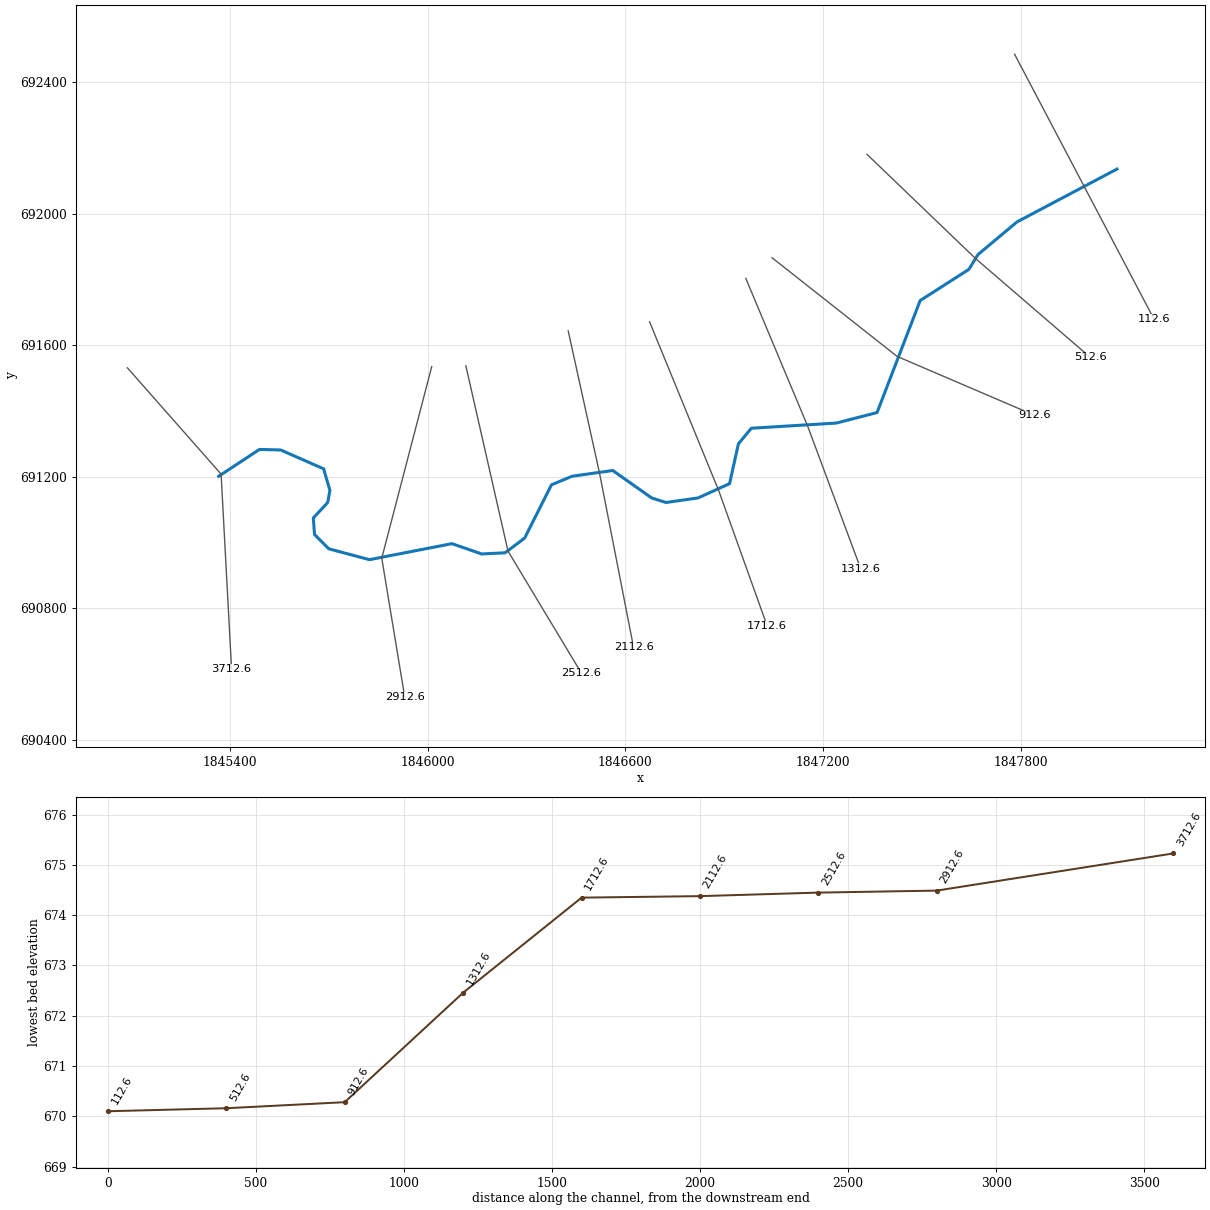
--- RFReedyCk1.prj (project) ---

Proj Title=RFReedyCk1
Current Plan=p01
Geom File=g01
Flow File=f01
Plan File=p01
DSS Export Rating Curves=0
DSS Export Rating Curve Sorted=0
DSS Export Volume Flow Curves=0
DXF OffsetX=0
DXF OffsetY=0
DXF ScaleX=0
DXF ScaleY=0

--- RFReedyCk1.p01 (plan) ---

Plan Title=Floodplain
Program Version=4.00
Geom File=g01
Flow File=f01
K Sum by GR=0
Std Step Tol=0.01
Critical Tol=0.01
Num of Std Step Trials=20
Max Error Tol=0.3
Flow Tol Ratio=0.001
Split Flow NTrial=30
Split Flow Tol=0.02
Split Flow Ratio=0.02
Log Output Level=0
Friction Slope Method=1
Unsteady Friction Slope Method=2
Unsteady Bridges Friction Slope Method=1
Global Log Level=0
CheckData=False
Run HTab=0
Run UNet=0
Run PostProcess=0
UNET Theta=0
UNET Theta Warmup=0
UNET ZTol=0
UNET ZSATol=0
UNET MxIter=0
UNET MaxInSteps=0
UNET DtIC=0
UNET DtMin=0
UNET MaxCRTS=0
UNET WFStab=0
UNET SFStab=0
UNET WFX=0
UNET SFX=0
UNET DSS MLevel=0
UNET DZMax Abort=0
UNET Convert EG Bridges=0
UNET Use Existing IB Tables=0
UNET Froude Limit=0
UNET Froude Power=0
Write IC File=0
Echo Input=False
Echo Output=False
Write Detailed=0

--- RFReedyCk1.f01 (steady flow) ---

Flow Title=NFF Regression Equation
Program Version=4.00
Number of Profiles=1
Profile Names=P100yr
River Rch & RM=RFReedyCk1,Main      ,3712.6
2858.562
River Rch & RM=RFReedyCk1,Main      ,512.6
2894.197
River Rch & RM=RFReedyCk1,Main      ,112.6
2907.717
Boundary for River Rch & Prof#=RFReedyCk1,Main      ,1
Up Type=0
Dn Type=3
Dn Slope=0.001831

--- RFReedyCk1.g01 (geometry) ---

Geom Title=USGS 3m DEM
Program Version=4.00

River Reach=RFReedyCk1     ,Main
Reach XY= 30
     1845366.202      691201.087     1845490.230      691282.854
     1845554.491      691281.122     1845684.753      691223.817
     1845703.863      691157.821     1845696.918      691121.348
     1845653.503      691074.452     1845657.101      691024.177
     1845700.402      690980.669     1845823.716      690947.680
     1846073.809      690996.328     1846164.124      690965.072
     1846235.332      690968.551     1846294.500      691013.328
     1846375.996      691175.238     1846438.518      691201.294
     1846561.828      691218.671     1846679.936      691135.314
     1846723.356      691121.423     1846820.615      691135.324
     1846916.135      691178.751     1846942.906      691299.553
     1846982.120      691347.224     1847240.292      691362.980
     1847363.628      691394.875     1847494.335      691735.330
     1847642.063      691830.097     1847669.848      691875.255
     1847787.942      691974.260     1848091.297      692135.015

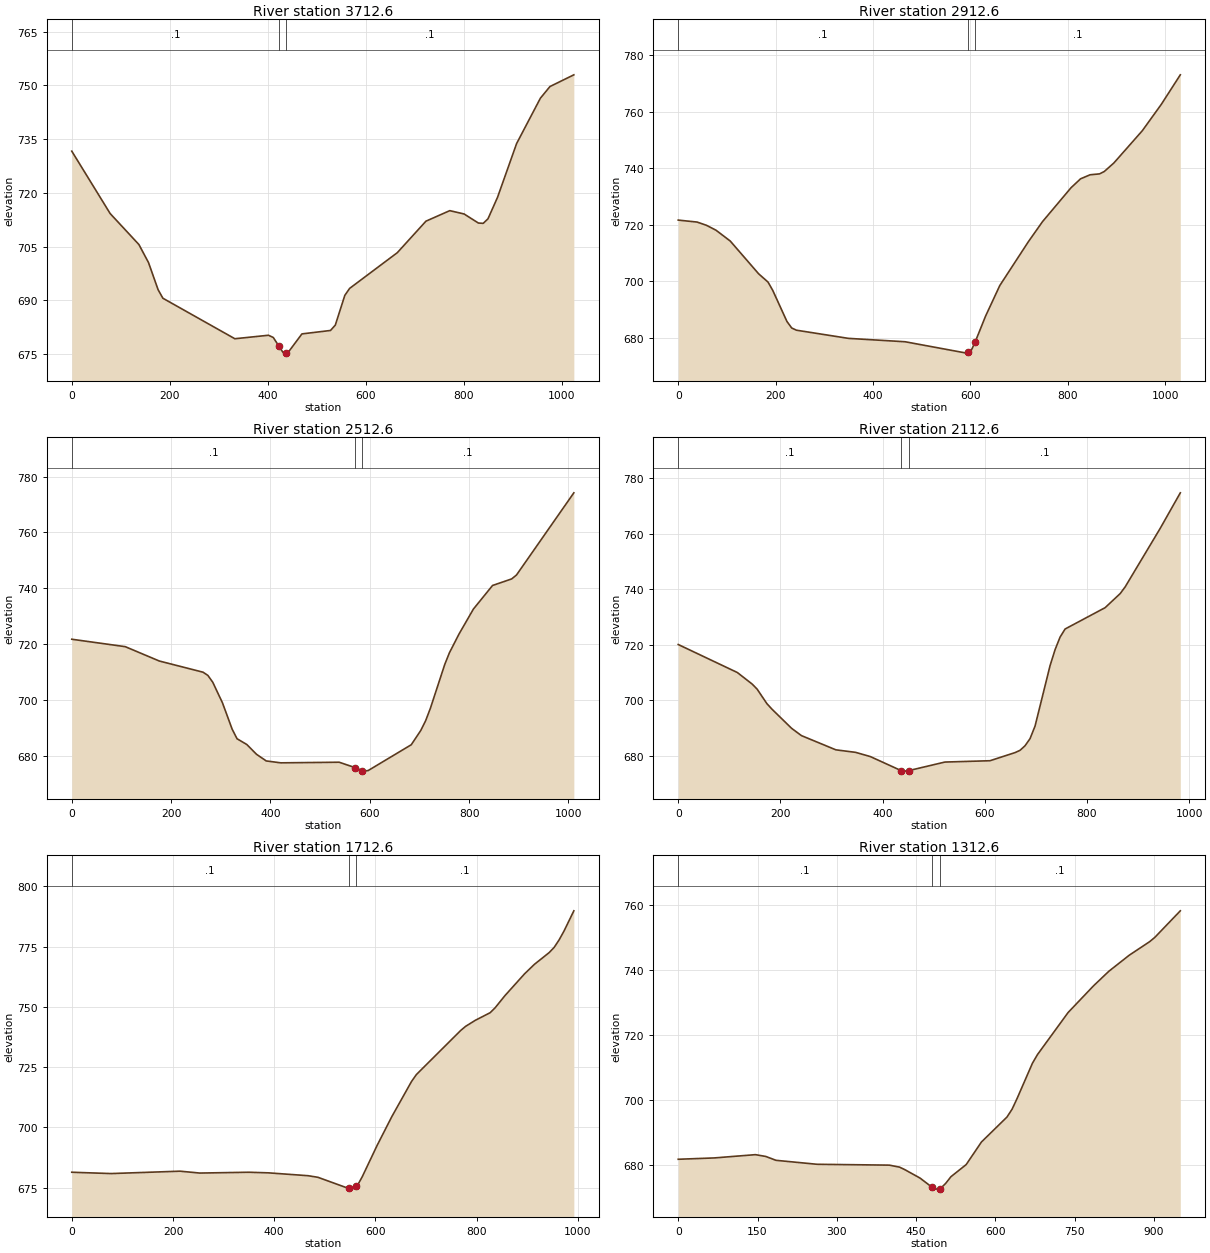
Type RM Length L Ch R = 1 ,3712.6,824.8,799.6,804.9
XS GIS Cut Line= 3
     1845089.375      691530.978     1845373.711      691207.691
     1845405.463      690614.910
#Sta/Elev= 30
       0  731.65    78.3  714.22   137.0  705.56   156.6  700.51   176.1  692.95
   185.9  690.56   332.7  679.25   401.2  680.22   411.0  679.61     423  677.09
   430.5  675.50     438  675.29   440.3  675.23   469.5  680.60   527.8  681.56
   537.6  683.06   557.0  691.36   566.8  693.31   664.1  703.29   722.5  712.09
   771.1  715.03   800.3  714.10   829.5  711.57   839.3  711.48   849.0  712.74
   868.5  718.74   907.4  733.76   956.0  746.45   975.5  749.70  1024.2  752.97
#Mann= 3 , 0 , 0
       0     0.1       0     423   0.045       0     438     0.1       0
Bank Sta=     423,     438
Exp/Cntr=0.3,0.1

Type RM Length L Ch R = 1 ,2912.6,385.8,399.8,408.4
XS GIS Cut Line= 3
     1846012.627      691534.478     1845861.080      690952.166
     1845930.969      690528.851
#Sta/Elev= 30
       0  721.64    38.8  720.94    58.2  719.78    77.6  718.05   106.8  714.22
   165.0  702.62   184.4  699.66   194.1  696.71   223.2  685.71   232.9  683.41
   242.6  682.62   349.4  679.72   465.8  678.52   592.0  674.49   594.2  674.72
   601.7  675.51   609.2  678.27   631.0  687.61   660.2  698.45   718.7  713.94
   748.0  721.12   806.5  733.12   826.0  736.27   845.5  737.70   865.0  738.02
   874.7  738.87   894.2  741.85   952.8  753.32   991.8  762.67  1030.8  773.13
#Mann= 3 , 0 , 0
       0     0.1       0   594.2   0.045       0   609.2     0.1       0
Bank Sta=   594.2,   609.2
Exp/Cntr=0.3,0.1

Type RM Length L Ch R = 1 ,2512.6,399.6,399.6,391.7
XS GIS Cut Line= 3
     1846116.198      691536.980     1846244.012      690973.760
     1846467.009      690602.160
#Sta/Elev= 30
       0  721.72   107.7  719.06   176.2  713.92   264.3  709.91   274.1  708.75
   283.9  706.30   303.4  698.94   323.0  689.46   332.8  686.05   352.4  684.00
   372.0  680.48   391.6  678.10   420.9  677.42   538.4  677.64     570  675.74
     585  674.57   587.2  674.45   596.8  674.66   683.5  683.90   702.7  689.02
   712.4  692.48   722.0  696.94   750.9  712.65   760.5  716.91   779.8  723.62
   808.7  732.54   847.2  740.99   885.7  743.34   895.4  744.74  1010.9  774.20
#Mann= 3 , 0 , 0
       0     0.1       0     570   0.045       0     585     0.1       0
Bank Sta=     570,     585
Exp/Cntr=0.3,0.1

Type RM Length L Ch R = 1 ,2112.6,396.1,400,403.4
XS GIS Cut Line= 3
     1846426.651      691643.116     1846521.847      691209.968
     1846625.021      690680.709
#Sta/Elev= 30
       0  720.04   115.7  709.94   144.6  705.79   154.3  703.98   173.5  698.73
   183.2  696.77   221.7  689.85   241.0  687.20   308.5  682.06   347.1  681.15
   376.0  679.63     436  674.59   443.5  674.38     451  674.56   521.9  677.65
   610.2  678.13   659.2  681.06   669.0  681.88   678.8  683.53   688.6  686.10
   698.4  690.63   727.8  712.44   737.6  718.18   747.4  722.72   757.2  725.63
   835.6  733.33   865.1  738.42   874.9  740.86   943.5  761.97   982.7  774.74
#Mann= 3 , 0 , 0
       0     0.1       0     436   0.045       0     451     0.1       0
Bank Sta=     436,     451
Exp/Cntr=0.3,0.1

Type RM Length L Ch R = 1 ,1712.6,399.6,399.9,400.3
XS GIS Cut Line= 3
     1846673.459      691670.901     1846883.211      691157.685
     1847030.373      690745.727
#Sta/Elev= 30
       0  681.36    77.8  680.81   214.0  681.80   252.9  681.02   350.2  681.36
   389.1  681.10   466.9  679.92   486.3  679.26   546.9  674.64   554.4  674.35
   561.9  675.47   564.2  675.81   573.9  679.50   603.0  692.39   632.2  704.41
   671.1  718.99   680.8  721.90   768.3  740.20   778.0  741.91   797.4  744.45
   826.6  747.59   836.3  749.61   855.8  754.68   894.7  763.76   914.1  767.68
   943.3  772.57   953.0  774.70   962.7  777.78   972.4  781.45   991.9  789.88
#Mann= 3 , 0 , 0
       0     0.1       0   546.9   0.045       0   561.9     0.1       0
Bank Sta=   546.9,   561.9
Exp/Cntr=0.3,0.1

Type RM Length L Ch R = 1 ,1312.6,389.2,400.4,418.1
XS GIS Cut Line= 3
     1846965.450      691802.694     1847153.118      691353.585
     1847314.126      690919.677
#Sta/Elev= 30
       0  681.67    68.1  682.08   146.0  683.09   165.5  682.54   185.0  681.34
   262.8  680.12   399.1  679.86   418.6  679.24   428.3  678.49   457.5  675.85
   479.2  673.14   486.7  672.46   494.2  672.65   496.4  672.70   506.0  674.26
   515.7  676.28   544.6  680.03   573.5  687.00   621.7  694.68   631.4  697.10
   641.0  700.45   669.9  711.28   679.6  713.99   737.4  726.93   785.6  735.18
   814.6  739.67   853.1  744.61   891.7  748.79   901.4  750.10   949.6  758.29
#Mann= 3 , 0 , 0
       0     0.1       0   479.2   0.045       0   494.2     0.1       0
Bank Sta=   479.2,   494.2
Exp/Cntr=0.3,0.1

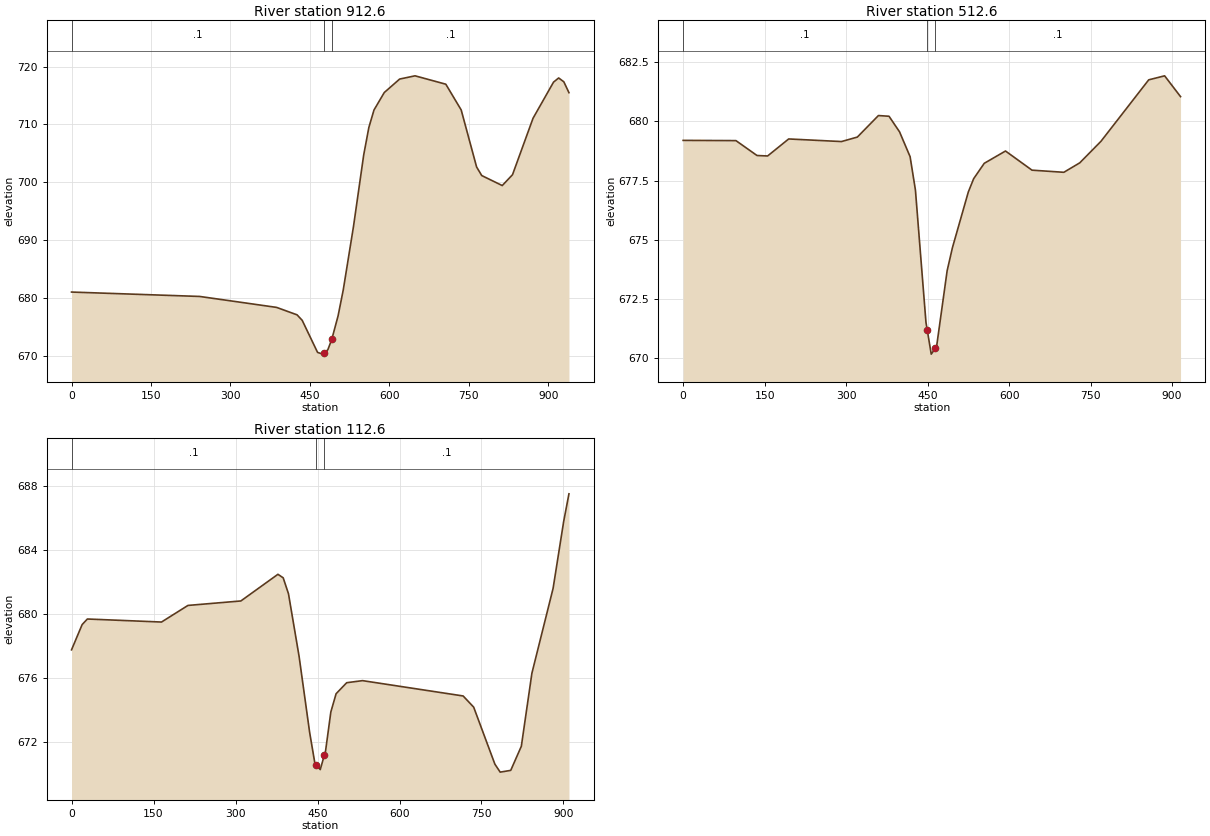
Type RM Length L Ch R = 1 ,912.6,401.4,399.4,393
XS GIS Cut Line= 3
     1847044.819      691865.662     1847424.290      691565.642
     1847842.463      691385.986
#Sta/Elev= 30
       0  681.01   241.9  680.25   387.0  678.36   425.7  677.07   435.4  676.12
   464.4  670.58   474.1  670.28   476.2  670.44   483.8  671.04   491.2  672.82
   503.1  676.88   512.8  681.34   532.2  692.34   551.5  704.72   561.2  709.46
   570.9  712.48   590.3  715.50   619.3  717.83   648.4  718.39   706.5  716.94
   735.5  712.49   764.6  702.63   774.3  701.15   813.0  699.42   832.4  701.30
   871.1  711.05   909.8  717.30   919.5  718.02   929.2  717.36   938.9  715.48
#Mann= 3 , 0 , 0
       0     0.1       0   476.2   0.045       0   491.2     0.1       0
Bank Sta=   476.2,   491.2
Exp/Cntr=0.3,0.1

Type RM Length L Ch R = 1 ,512.6,407.2,400,391.5
XS GIS Cut Line= 3
     1847333.206      692179.676     1847662.362      691863.088
     1848009.735      691563.264
#Sta/Elev= 30
       0  679.20    97.2  679.19   136.0  678.56   155.5  678.54   194.3  679.26
   291.5  679.15   320.7  679.34   359.5  680.25   379.0  680.22   398.4  679.56
   417.8  678.51   427.6  677.10   447.0  671.50   449.2  671.20   456.7  670.16
   464.2  670.40   466.5  670.47   486.0  673.69   495.8  674.67   525.0  677.02
   534.8  677.58   554.3  678.23   593.4  678.75   642.2  677.94   700.8  677.85
   730.1  678.25   769.1  679.16   857.0  681.76   886.3  681.93   915.6  681.05
#Mann= 3 , 0 , 0
       0     0.1       0   449.2   0.045       0   464.2     0.1       0
Bank Sta=   449.2,   464.2
Exp/Cntr=0.3,0.1

Type RM Length L Ch R = 1 ,112.6,112.3,112.5,112.8
XS GIS Cut Line= 3
     1847780.909      692484.046     1847992.437      692081.205
     1848203.965      691678.364
#Sta/Elev= 30
       0  677.76    19.4  679.34    29.0  679.69   164.6  679.50   213.0  680.54
   309.8  680.82   377.6  682.49   387.2  682.27   396.9  681.27   416.3  677.35
   435.6  672.59   445.3  670.63   447.5  670.55   455.0  670.26   462.5  671.16
   464.7  671.42   474.4  673.87   484.0  675.01   503.4  675.70   532.4  675.83
   716.4  674.87   735.7  674.17   774.5  670.60   784.2  670.10   803.5  670.21
   822.9  671.72   842.2  676.29   881.0  681.61   900.3  685.79   910.0  687.53
#Mann= 3 , 0 , 0
       0     0.1       0   447.5   0.045       0   462.5     0.1       0
Bank Sta=   447.5,   462.5
Exp/Cntr=0.3,0.1